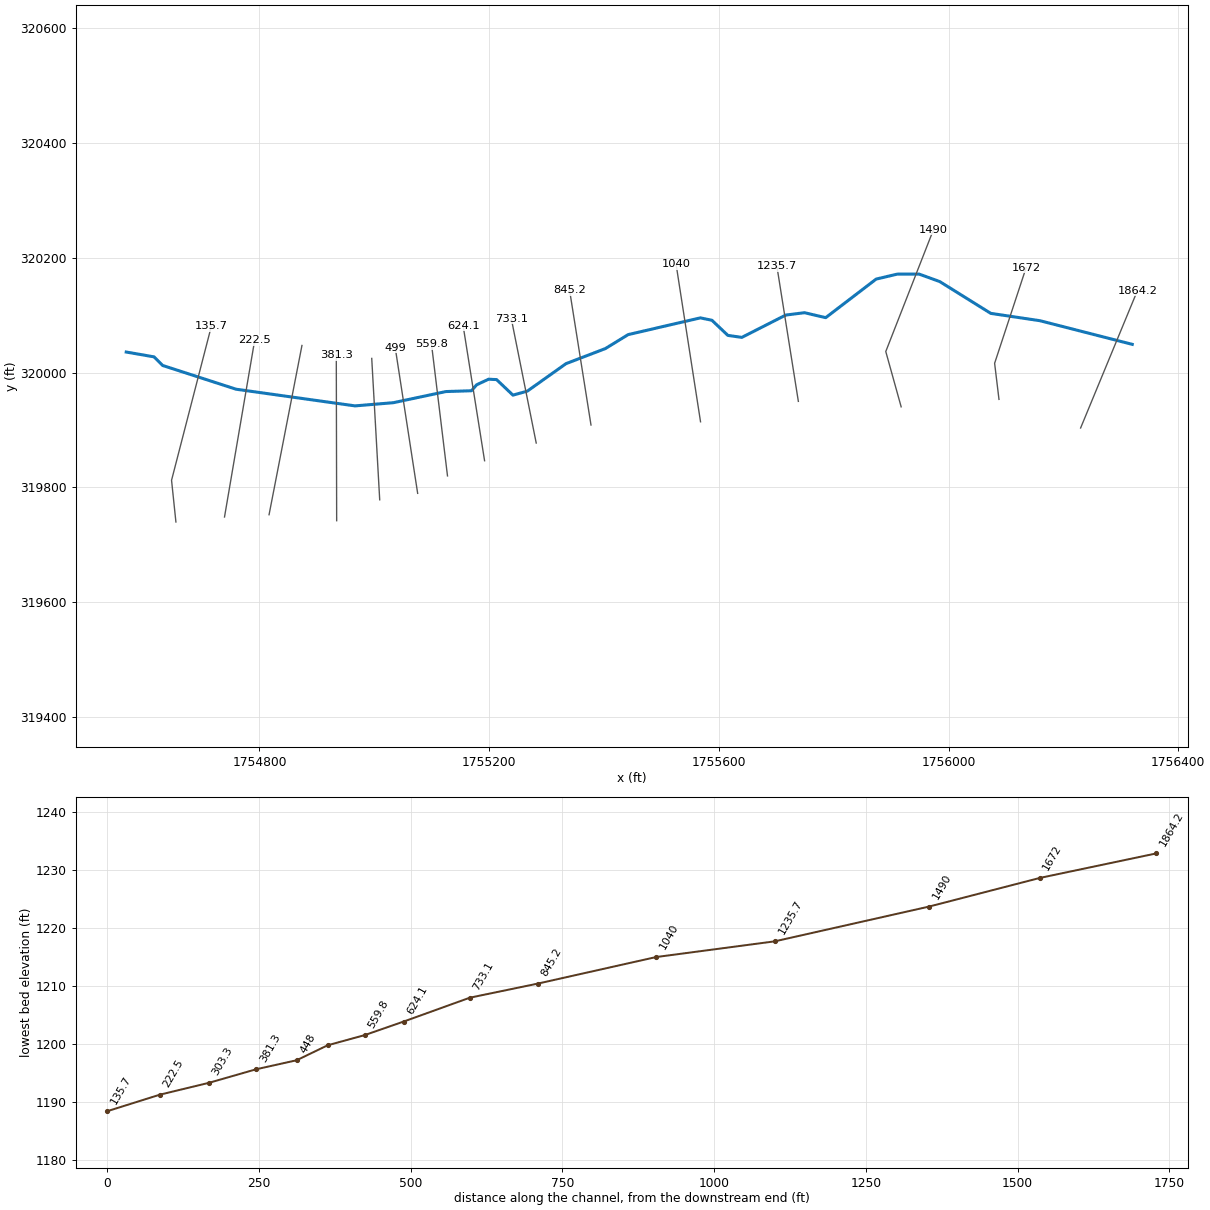
--- JIGLYBR.prj (project) ---

Proj Title=JIGLYBR
Current Plan=p01
Default Exp/Contr=0,0
English Units
Geom File=g01
Flow File=f01
Plan File=p01
BEGIN DESCRIPTION:
END DESCRIPTION:
DSS Export Rating Curves= 0
DSS Export Rating Curve Sorted= 0
DSS Export Volume Flow Curves= 0
DXF OffsetX= 0
DXF OffsetY= 0
DXF ScaleX= 0
DXF ScaleY= 0

--- JIGLYBR.p01 (plan) ---

Plan Title=Floodplain
Program Version=4.00
Geom File=g01
Flow File=f01
K Sum by GR=0
Std Step Tol=0.01
Critical Tol=0.01
Num of Std Step Trials=20
Max Error Tol=0.3
Flow Tol Ratio=0.001
Split Flow NTrial=30
Split Flow Tol=0.02
Split Flow Ratio=0.02
Log Output Level=0
Friction Slope Method=1
Unsteady Friction Slope Method=2
Unsteady Bridges Friction Slope Method=1
Global Log Level=0
CheckData=False
Run HTab=0
Run UNet=0
Run PostProcess=0
UNET Theta=0
UNET Theta Warmup=0
UNET ZTol=0
UNET ZSATol=0
UNET MxIter=0
UNET MaxInSteps=0
UNET DtIC=0
UNET DtMin=0
UNET MaxCRTS=0
UNET WFStab=0
UNET SFStab=0
UNET WFX=0
UNET SFX=0
UNET DSS MLevel=0
UNET DZMax Abort=0
UNET Convert EG Bridges=0
UNET Use Existing IB Tables=0
UNET Froude Limit=0
UNET Froude Power=0
Write IC File=0
Echo Input=False
Echo Output=False
Write Detailed=0

--- JIGLYBR.f01 (steady flow) ---

Flow Title=NFF Regression Equation
Program Version=4.00
Number of Profiles=1
Profile Names=P100yr
River Rch & RM=JIGLYBR,Main      ,1864.2
887.5405
River Rch & RM=JIGLYBR,Main      ,559.8
918.6663
River Rch & RM=JIGLYBR,Main      ,222.5
923.4176
Boundary for River Rch & Prof#=JIGLYBR,Main      ,1
Up Type=0
Dn Type=3
Dn Slope=0.027914

--- JIGLYBR.g01 (geometry) ---

Geom Title=USGS 10m DEM
Program Version=4.10

River Reach=JIGLYBR         ,Main
Reach XY= 30
     1756319.953      320049.169     1756159.162      320090.395
     1756073.609      320103.172     1755984.656       320158.63
     1755948.848      320171.651     1755910.871      320171.651
     1755873.979      320162.971     1755786.088      320095.696
     1755749.066      320104.355     1755716.427      320100.189
     1755640.038        320061.3     1755615.732      320064.772
     1755587.954      320091.161     1755567.815      320095.327
     1755442.121      320066.161     1755402.538      320041.855
     1755333.788      320015.466     1755266.427       319967.55
     1755241.427      319960.606     1755212.954      319987.689
     1755199.066      319988.383     1755178.232      319978.661
     1755169.204      319968.244      1755124.76      319966.856
     1755033.094      319947.411     1754966.427      319941.855
     1754759.203      319970.948     1754631.375       320012.35
     1754616.368      320027.357     1754567.959      320035.771

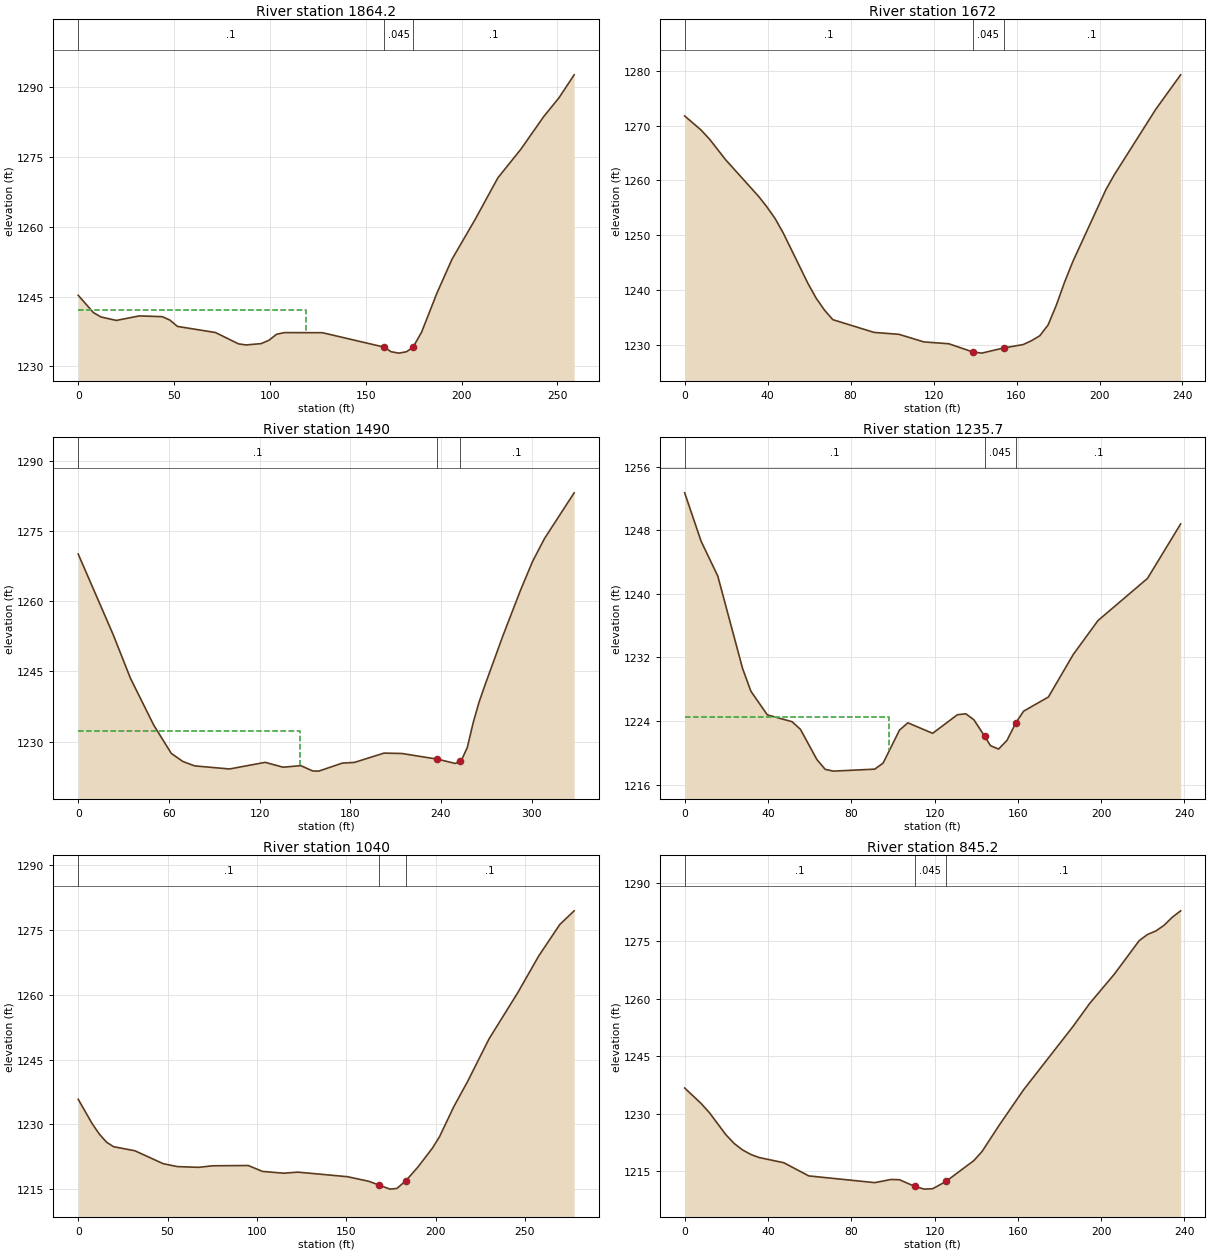
Type RM Length L Ch R = 1 ,1864.2  ,190.6,192.2,193.8
XS GIS Cut Line= 2
     1756230.016      319903.297     1756328.757      320142.446
#Sta/Elev= 30
       0 1245.26       8 1241.52    11.9  1240.6    19.9 1239.86    31.8 1240.83
    43.8 1240.67    47.8 1239.94    51.8 1238.57    71.6 1237.26    83.6 1234.82
    87.6 1234.59    95.5 1234.88    99.5  1235.6   103.5 1236.89   107.5 1237.24
   127.4 1237.22   159.6 1234.12   163.2 1233.13   167.2 1232.83   171.2 1233.12
   174.6 1234.06   179.1 1237.32   187.1 1245.71     195 1253.03     207 1261.53
   218.9  1270.5   230.9 1276.66   242.8 1283.66   250.8 1287.72   258.7 1292.65
#Mann= 3 , 0 , 0
       0      .1       0   159.6    .045       0   174.6      .1       0
#XS Ineff= 2 , 0
          119.05 1242.16
Permanent Ineff=
       F       F
Bank Sta=159.6,174.6
XS Rating Curve= 0 ,0
Exp/Cntr=0.3,0.1

Type RM Length L Ch R = 1 ,1672    ,183.6,182,180.5
XS GIS Cut Line= 3
     1756087.872       319953.21     1756080.276      320016.144
     1756135.181      320183.028
#Sta/Elev= 30
       0 1271.74     7.9 1269.18    11.9 1267.56    19.8 1263.75    35.7 1257.09
    39.6 1255.22    43.6 1253.08    47.5 1250.47    59.4  1241.3    63.4 1238.59
    67.4 1236.43    71.4 1234.69    91.3 1232.37   103.3 1232.02   115.3 1230.64
   127.3 1230.31   138.8 1228.83   143.2  1228.6   153.8 1229.54   163.2 1230.16
   167.2 1230.86   171.2 1231.76   175.2 1233.72   179.2 1237.34   183.2 1241.56
   187.2 1245.31   203.1 1258.35   207.1 1261.02   227.1 1272.94   239.1 1279.22
#Mann= 3 , 0 , 0
       0      .1       0   138.8    .045       0   153.8      .1       0
Bank Sta=138.8,153.8
XS Rating Curve= 0 ,0
Exp/Cntr=0.3,0.1

Type RM Length L Ch R = 1 ,1490    ,242.8,254.3,265.1
XS GIS Cut Line= 3
     1755917.516      319940.189     1755890.714      320036.634
     1755973.722         320249.
#Sta/Elev= 30
       0 1270.06    23.1 1252.87    34.6 1243.49      50 1233.49    61.6 1227.46
    69.3 1225.73      77  1224.8   100.1 1224.14   123.7 1225.56   135.5 1224.52
   147.3 1224.85   155.1 1223.72   159.1 1223.68   174.8  1225.4   182.7 1225.54
   202.3 1227.53   214.1 1227.45   237.6 1226.24   249.5 1225.32   252.6  1225.8
   253.4 1225.92   257.4 1228.71   261.3 1234.04   265.2 1238.43   269.1 1242.06
   280.9 1252.54   292.7  1262.4   300.6 1268.49   308.5 1273.38   328.1 1283.14
#Mann= 3 , 0 , 0
       0      .1       0   237.6    .045       0   252.6      .1       0
#XS Ineff= 2 , 0
          146.41 1232.34
Permanent Ineff=
       F       F
Bank Sta=237.6,252.6
XS Rating Curve= 0 ,0
Exp/Cntr=0.3,0.1

Type RM Length L Ch R = 1 ,1235.7  ,195.4,195.7,195.7
XS GIS Cut Line= 2
     1755738.479      319949.738     1755701.153      320184.981
#Sta/Elev= 30
       0 1252.72     7.9 1246.62    15.9 1242.25    27.8 1230.62    31.8 1227.75
    39.7 1224.77    51.6 1223.91    55.6 1222.95    63.5 1219.15    67.5 1217.91
    71.5 1217.69    91.3 1217.94    95.3  1218.7   103.2 1222.86   107.2 1223.77
   119.1 1222.45     131 1224.79     135 1224.91   138.9 1224.16   144.1 1222.07
   146.9 1220.89   150.8 1220.47   154.8 1221.56   159.1 1223.79   162.8 1225.24
   174.7 1227.02   186.6 1232.36   198.5 1236.64   222.3 1241.95   238.2  1248.8
#Mann= 3 , 0 , 0
       0      .1       0   144.1    .045       0   159.1      .1       0
#XS Ineff= 2 , 0
           98.36  1224.5
Permanent Ineff=
       F       F
Bank Sta=144.1,159.1
XS Rating Curve= 0 ,0
Exp/Cntr=0.3,0.1

Type RM Length L Ch R = 1 ,1040    ,194.7,194.8,194.8
XS GIS Cut Line= 2
     1755568.124      319914.148     1755525.589      320188.453
#Sta/Elev= 30
       0  1235.8     7.9 1230.09    11.9 1227.69    15.9 1225.84    19.8 1224.81
    31.7 1223.87    47.6 1220.87    55.5  1220.2    67.4 1220.03    75.3 1220.39
    95.2 1220.45   103.1 1219.09     115 1218.67   122.9 1218.92   150.7 1217.86
   162.6  1216.8   168.4 1215.92   174.5 1214.98   178.4 1215.14   183.4 1216.93
   190.3 1220.17   198.3 1224.51   202.2 1227.09   210.2 1234.06   218.1 1240.03
     230 1249.82   245.9  1260.4   257.8 1269.02   269.6 1276.31   277.6 1279.46
#Mann= 3 , 0 , 0
       0      .1       0   168.4    .045       0   183.4      .1       0
Bank Sta=168.4,183.4
XS Rating Curve= 0 ,0
Exp/Cntr=0.3,0.1

Type RM Length L Ch R = 1 ,845.2   ,111.1,112.1,112.7
XS GIS Cut Line= 2
     1755377.368      319908.505     1755340.042      320143.748
#Sta/Elev= 30
       0 1236.72     7.9 1232.69    11.9 1230.29    19.8 1224.55    23.8 1222.27
    27.8  1220.6    31.8 1219.42    35.7 1218.64    47.6 1217.28    59.6 1213.85
    91.3  1212.1    99.2 1212.93   103.2 1212.85   110.5 1211.12   115.1 1210.41
   119.1 1210.51   125.5 1212.41   138.9 1217.84   142.9 1220.25   150.8 1226.83
   162.8 1236.27   186.6 1252.79   194.5  1258.7   206.4 1266.36   218.3 1275.05
   222.3 1276.66   226.3 1277.57   230.2 1279.03   234.2 1281.14   238.2 1282.81
#Mann= 3 , 0 , 0
       0      .1       0   110.5    .045       0   125.5      .1       0
Bank Sta=110.5,125.5
XS Rating Curve= 0 ,0
Exp/Cntr=0.3,0.1

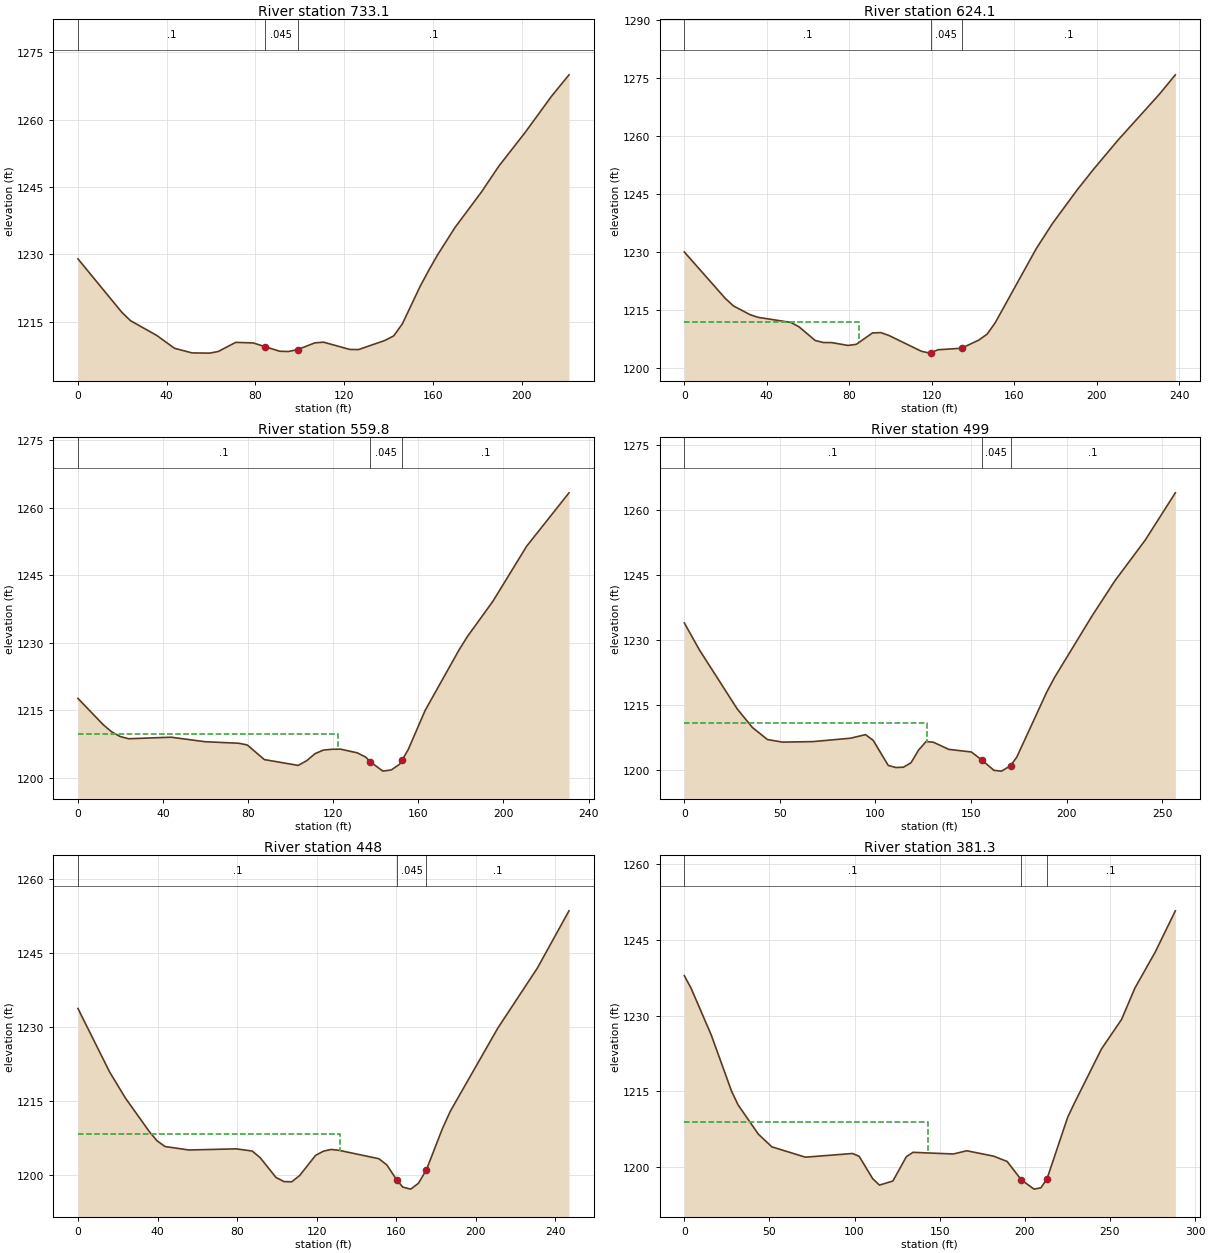
Type RM Length L Ch R = 1 ,733.1   ,112.3,109,104.9
XS GIS Cut Line= 2
     1755281.973      319877.056      1755238.57       320094.07
#Sta/Elev= 30
       0 1228.97    19.8 1217.06    23.7  1215.2    35.6 1211.89    43.5 1209.06
    51.4 1208.03    59.3 1207.98    63.2 1208.34    71.1 1210.38      79 1210.25
    84.1 1209.45    90.9  1208.4    94.8 1208.34    99.1 1208.78   106.7 1210.26
   110.7 1210.42   122.5  1208.8   126.5 1208.78   138.3  1210.8   142.3 1211.82
   146.2  1214.5   154.1 1222.74   158.1 1226.43     162 1229.81   169.9 1235.95
   181.8 1243.84   189.7 1249.64   201.6 1257.18   213.4 1265.18   221.3 1269.97
#Mann= 3 , 0 , 0
       0      .1       0    84.1    .045       0    99.1      .1       0
Bank Sta=84.1,99.1
XS Rating Curve= 0 ,0
Exp/Cntr=0.3,0.1

Type RM Length L Ch R = 1 ,624.1   ,64.1,64.4,65
XS GIS Cut Line= 2
     1755192.038      319846.222     1755154.712      320081.465
#Sta/Elev= 30
       0 1230.03    19.8 1218.06    23.8 1216.09    31.8 1213.84    35.7 1213.13
    51.6 1211.82    55.6  1210.7    63.5 1207.14    67.5 1206.61    71.5 1206.59
    79.4 1205.86    83.4 1206.14    91.3 1209.09    95.3 1209.18    99.2 1208.45
   115.1 1204.33   119.1 1203.87   119.5 1203.96   123.1 1204.74   134.5 1205.14
   142.9 1207.26   146.9 1208.78   150.8 1211.71   170.7 1230.86   178.6  1237.4
   190.6 1246.09   198.5  1251.4   210.4 1258.96   230.2 1270.66   238.2 1275.83
#Mann= 3 , 0 , 0
       0      .1       0   119.5    .045       0   134.5      .1       0
#XS Ineff= 2 , 0
           84.93    1212
Permanent Ineff=
       F       F
Bank Sta=119.5,134.5
XS Rating Curve= 0 ,0
Exp/Cntr=0.3,0.1

Type RM Length L Ch R = 1 ,559.8   ,60,60.7,61.4
XS GIS Cut Line= 2
     1755127.459      319819.765     1755099.681      320048.931
#Sta/Elev= 30
       0 1217.67    11.9 1211.82    15.9 1210.23    19.9  1209.2    23.9 1208.72
    43.8 1209.06    59.7 1208.06    75.6 1207.72    79.6 1207.33    87.6 1204.09
   103.5  1202.8   107.5 1203.84   111.4  1205.4   115.4 1206.21   119.4 1206.38
   123.4 1206.41   131.3 1205.59   135.3 1204.63   137.3 1203.65   143.3 1201.53
   147.3  1201.8   151.2 1203.07   152.3 1203.95   155.2 1206.28   163.2 1215.02
   179.1 1228.42   183.1 1231.44     195 1239.21   210.9 1251.46   230.8 1263.31
#Mann= 3 , 0 , 0
       0      .1       0   137.3    .045       0   152.3      .1       0
#XS Ineff= 2 , 0
          122.39 1209.71
Permanent Ineff=
       F       F
Bank Sta=137.3,152.3
XS Rating Curve= 0 ,0
Exp/Cntr=0.3,0.1

Type RM Length L Ch R = 1 ,499     ,53.3,51.1,48.9
XS GIS Cut Line= 2
     1755075.502      319789.365      1755036.44      320043.271
#Sta/Elev= 30
       0 1233.94     7.9 1227.73    27.7 1214.11    35.6 1209.86    43.5 1207.07
    51.4 1206.47    67.2 1206.59      87 1207.38    94.8  1208.2    98.8 1206.89
   106.7  1201.1   110.7 1200.62   114.6 1200.69   118.6 1201.71   122.5 1204.61
   126.5 1206.61   130.4 1206.44   138.3 1204.81   150.2  1204.2   155.7 1202.33
     162 1199.97     166 1199.79   170.7 1201.05   173.9 1202.98   189.7 1218.08
   193.7 1221.38   213.4 1235.61   225.3 1243.66   241.1    1253   256.9 1263.92
#Mann= 3 , 0 , 0
       0      .1       0   155.7    .045       0   170.7      .1       0
#XS Ineff= 2 , 0
          127.19  1210.8
Permanent Ineff=
       F       F
Bank Sta=155.7,170.7
XS Rating Curve= 0 ,0
Exp/Cntr=0.3,0.1

Type RM Length L Ch R = 1 ,448     ,67.7,66.6,65.3
XS GIS Cut Line= 2
     1755009.403      319778.098     1754995.514      320024.626
#Sta/Elev= 30
       0 1233.81    15.9 1220.96    23.9 1215.64    35.8 1208.91    39.8 1206.99
    43.8 1205.84    55.8 1205.14    79.6 1205.37    87.6 1204.93    91.6 1203.59
    99.6 1199.56   103.6 1198.74   107.5 1198.69   111.5 1199.98   119.5 1204.06
   123.5 1204.91   127.4 1205.25   131.4 1205.06   151.3 1203.37   155.3 1202.12
   160.2 1199.14   163.3 1197.62   167.3 1197.21   171.2 1198.39   175.2 1201.12
   183.2 1209.42   187.2 1212.97   211.1 1229.83     231    1242   246.9  1253.6
#Mann= 3 , 0 , 0
       0      .1       0   160.2    .045       0   175.2      .1       0
#XS Ineff= 2 , 0
             132 1208.29
Permanent Ineff=
       F       F
Bank Sta=160.2,175.2
XS Rating Curve= 0 ,0
Exp/Cntr=0.3,0.1

Type RM Length L Ch R = 1 ,381.3   ,82.5,78,73.7
XS GIS Cut Line= 2
     1754934.443      319741.622     1754933.792      320030.033
#Sta/Elev= 30
       0 1237.95       4 1235.44    15.8 1226.21    27.7 1215.11    31.6 1212.34
    43.5 1206.55    51.4 1204.04    71.1 1201.99    98.8 1202.72   102.7 1202.16
   110.6 1197.75   114.6 1196.46   122.5 1197.26   130.4 1202.08   134.3 1202.95
     158 1202.62   165.9 1203.26   181.7 1202.19   189.6 1201.14     198 1197.48
   205.4 1195.66   209.4 1195.92     213 1197.68   225.2 1209.93   229.2 1212.75
     245 1223.42   256.8 1229.27   264.7 1235.52   276.6 1242.63   288.4 1250.79
#Mann= 3 , 0 , 0
       0      .1       0     198    .045       0     213      .1       0
#XS Ineff= 2 , 0
          143.13 1208.99
Permanent Ineff=
       F       F
Bank Sta=198,213
XS Rating Curve= 0 ,0
Exp/Cntr=0.3,0.1

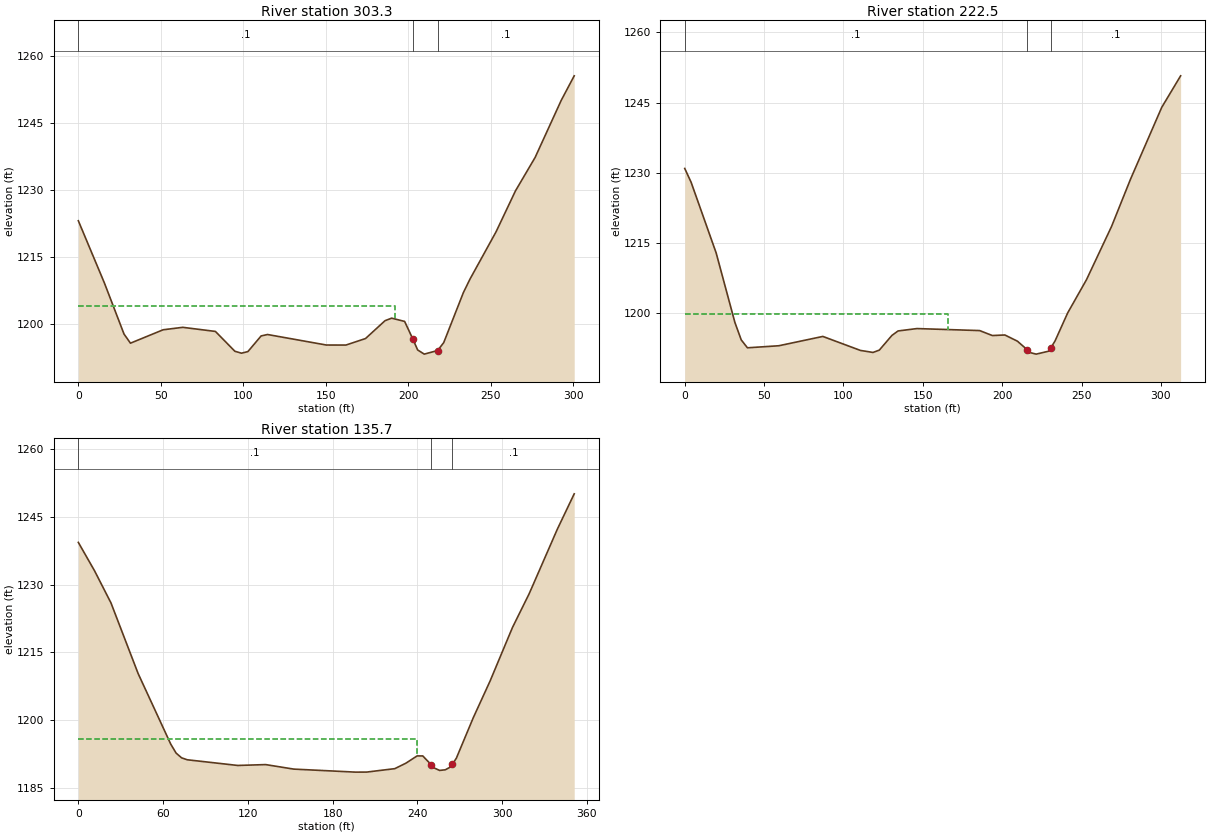
Type RM Length L Ch R = 1 ,303.3   ,80.2,80.8,81.2
XS GIS Cut Line= 2
     1754816.695      319752.056     1754873.987      320047.195
#Sta/Elev= 30
       0 1223.17    15.8 1209.25    27.7 1197.81    31.6 1195.77    51.4 1198.77
    63.3 1199.32    83.1  1198.4    94.9 1193.96    98.9 1193.53   102.8 1193.89
   110.8 1197.39   114.7 1197.71   150.3 1195.36   162.2 1195.35   174.1 1196.81
   185.9  1200.8   189.9 1201.37   197.8 1200.64   202.8 1196.68   205.7 1194.25
   209.7 1193.32   217.8 1194.13   221.5  1195.9   233.4 1207.08   237.4  1210.1
   253.2 1220.68     265 1229.87   276.9 1237.34   292.7  1250.1   300.6 1255.61
#Mann= 3 , 0 , 0
       0      .1       0   202.8    .045       0   217.8      .1       0
#XS Ineff= 2 , 0
          191.92    1204
Permanent Ineff=
       F       F
Bank Sta=202.8,217.8
XS Rating Curve= 0 ,0
Exp/Cntr=0.3,0.1

Type RM Length L Ch R = 1 ,222.5   ,88.8,86.8,85
XS GIS Cut Line= 2
      1754739.13      319748.132     1754791.648      320056.075
#Sta/Elev= 30
       0 1230.94       4 1228.01    19.8 1212.89    31.6 1198.05    35.6 1194.32
    39.5 1192.63    59.3 1193.07      87 1195.06   110.7 1192.07   118.6 1191.64
   122.6 1192.14   130.5 1195.27   134.4 1196.23   146.3 1196.74   185.8 1196.31
   193.8 1195.25   201.7 1195.37   209.6 1194.04   215.7 1192.24   217.5 1191.61
   221.4 1191.28   229.4 1191.92   230.7 1192.65   233.3  1194.1   241.2 1200.05
   253.1 1207.18   268.9 1218.56   280.8 1228.62   300.5 1243.99   312.4 1250.73
#Mann= 3 , 0 , 0
       0      .1       0   215.7    .045       0   230.7      .1       0
#XS Ineff= 2 , 0
           165.6 1199.89
Permanent Ineff=
       F       F
Bank Sta=215.7,230.7
XS Rating Curve= 0 ,0
Exp/Cntr=0.3,0.1

Type RM Length L Ch R = 1 ,135.7   ,133.5,135.7,137.6
XS GIS Cut Line= 3
     1754654.495      319739.452       1754646.9      319812.151
     1754716.344      320081.248
#Sta/Elev= 30
       0 1239.38    11.5 1233.07    23.1 1225.96    42.3 1210.31    65.4 1194.65
    69.2 1192.65    73.1  1191.6    77.1 1191.17   112.8 1189.91   132.6  1190.1
   152.5  1189.1   196.2 1188.43   204.1 1188.44     224  1189.2   231.9 1190.42
   239.8 1192.03   243.8 1192.02   249.8 1190.07   251.8 1189.37   255.7 1188.81
   259.7 1188.94   263.7 1189.62   264.8 1190.16   267.6 1191.54   279.6 1200.53
   291.5 1208.67   307.3 1220.51   319.2 1228.05   339.1 1242.34     351 1250.15
#Mann= 3 , 0 , 0
       0      .1       0   249.8    .045       0   264.8      .1       0
#XS Ineff= 2 , 0
          239.46  1195.8
Permanent Ineff=
       F       F
Bank Sta=249.8,264.8
XS Rating Curve= 0 ,0
Exp/Cntr=0.3,0.1

Chan Stop Cuts=-1
Use User Specified Reach Order=0
Composite Channel Slope=5